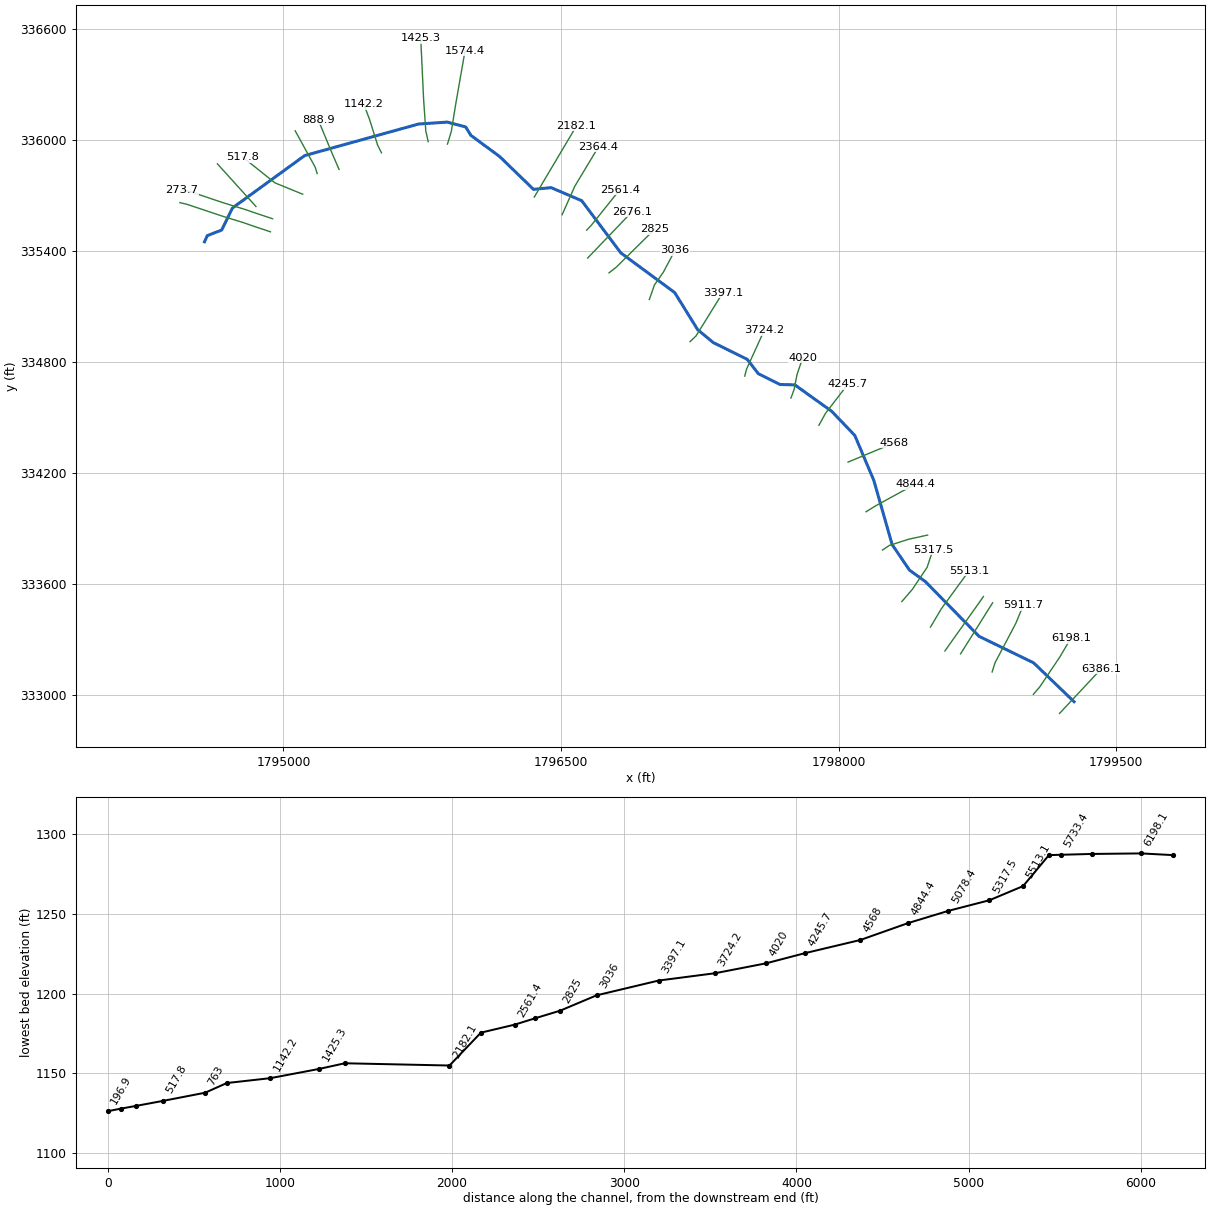
--- JAMESCK.prj (project) ---

Proj Title=JAMESCK
Current Plan=p01
Default Exp/Contr=0,0
English Units
Geom File=g01
Flow File=f01
Plan File=p01
BEGIN DESCRIPTION:
END DESCRIPTION:
DSS Export Rating Curves= 0
DSS Export Rating Curve Sorted= 0
DSS Export Volume Flow Curves= 0
DXF OffsetX= 0
DXF OffsetY= 0
DXF ScaleX= 0
DXF ScaleY= 0

--- JAMESCK.p01 (plan) ---

Plan Title=Floodplain
Program Version=4.00
Geom File=g01
Flow File=f01
K Sum by GR=0
Std Step Tol=0.01
Critical Tol=0.01
Num of Std Step Trials=20
Max Error Tol=0.3
Flow Tol Ratio=0.001
Split Flow NTrial=30
Split Flow Tol=0.02
Split Flow Ratio=0.02
Log Output Level=0
Friction Slope Method=1
Unsteady Friction Slope Method=2
Unsteady Bridges Friction Slope Method=1
Global Log Level=0
CheckData=False
Run HTab=0
Run UNet=0
Run PostProcess=0
UNET Theta=0
UNET Theta Warmup=0
UNET ZTol=0
UNET ZSATol=0
UNET MxIter=0
UNET MaxInSteps=0
UNET DtIC=0
UNET DtMin=0
UNET MaxCRTS=0
UNET WFStab=0
UNET SFStab=0
UNET WFX=0
UNET SFX=0
UNET DSS MLevel=0
UNET DZMax Abort=0
UNET Convert EG Bridges=0
UNET Use Existing IB Tables=0
UNET Froude Limit=0
UNET Froude Power=0
Write IC File=0
Echo Input=False
Echo Output=False
Write Detailed=0

--- JAMESCK.f01 (steady flow) ---

Flow Title=NFF Regression Equation
Program Version=4.00
Number of Profiles=1
Profile Names=P100yr
River Rch & RM=JAMESCK,Main      ,6386.1
980.2628
River Rch & RM=JAMESCK,Main      ,5317.5
1043.423
River Rch & RM=JAMESCK,Main      ,4020
1141.238
River Rch & RM=JAMESCK,Main      ,1574.4
1181.446
River Rch & RM=JAMESCK,Main      ,1142.2
1578.352
Boundary for River Rch & Prof#=JAMESCK,Main      ,1
Up Type=0
Dn Type=3
Dn Slope=0.020219

--- JAMESCK.g01 (geometry) ---

Geom Title=USGS 10m DEM
Program Version=4.10

River Reach=JAMESCK         ,Main
Reach XY= 30
     1799273.131      332961.831     1799054.407      333171.976
     1798759.431      333315.228     1798469.791      333610.838
     1798383.935      333672.574     1798289.652      333811.218
      1798190.52      334158.741     1798087.932      334401.078
      1797962.92      334531.613     1797764.088      334674.149
     1797683.793      334676.319     1797566.798      334734.443
     1797506.552      334812.262     1797323.301      334902.632
     1797238.453       334972.92     1797114.446       335173.24
     1796823.253      335387.618     1796611.888      335669.773
     1796446.478      335740.207     1796351.328      335731.006
     1796167.742       335908.87     1796012.894      336022.674
     1795984.741      336068.296     1795884.748      336094.505
     1795730.006      336084.034     1795114.444       335913.48
     1794724.169      335630.322     1794665.871      335510.939
     1794588.055      335480.842     1794573.099       335447.51

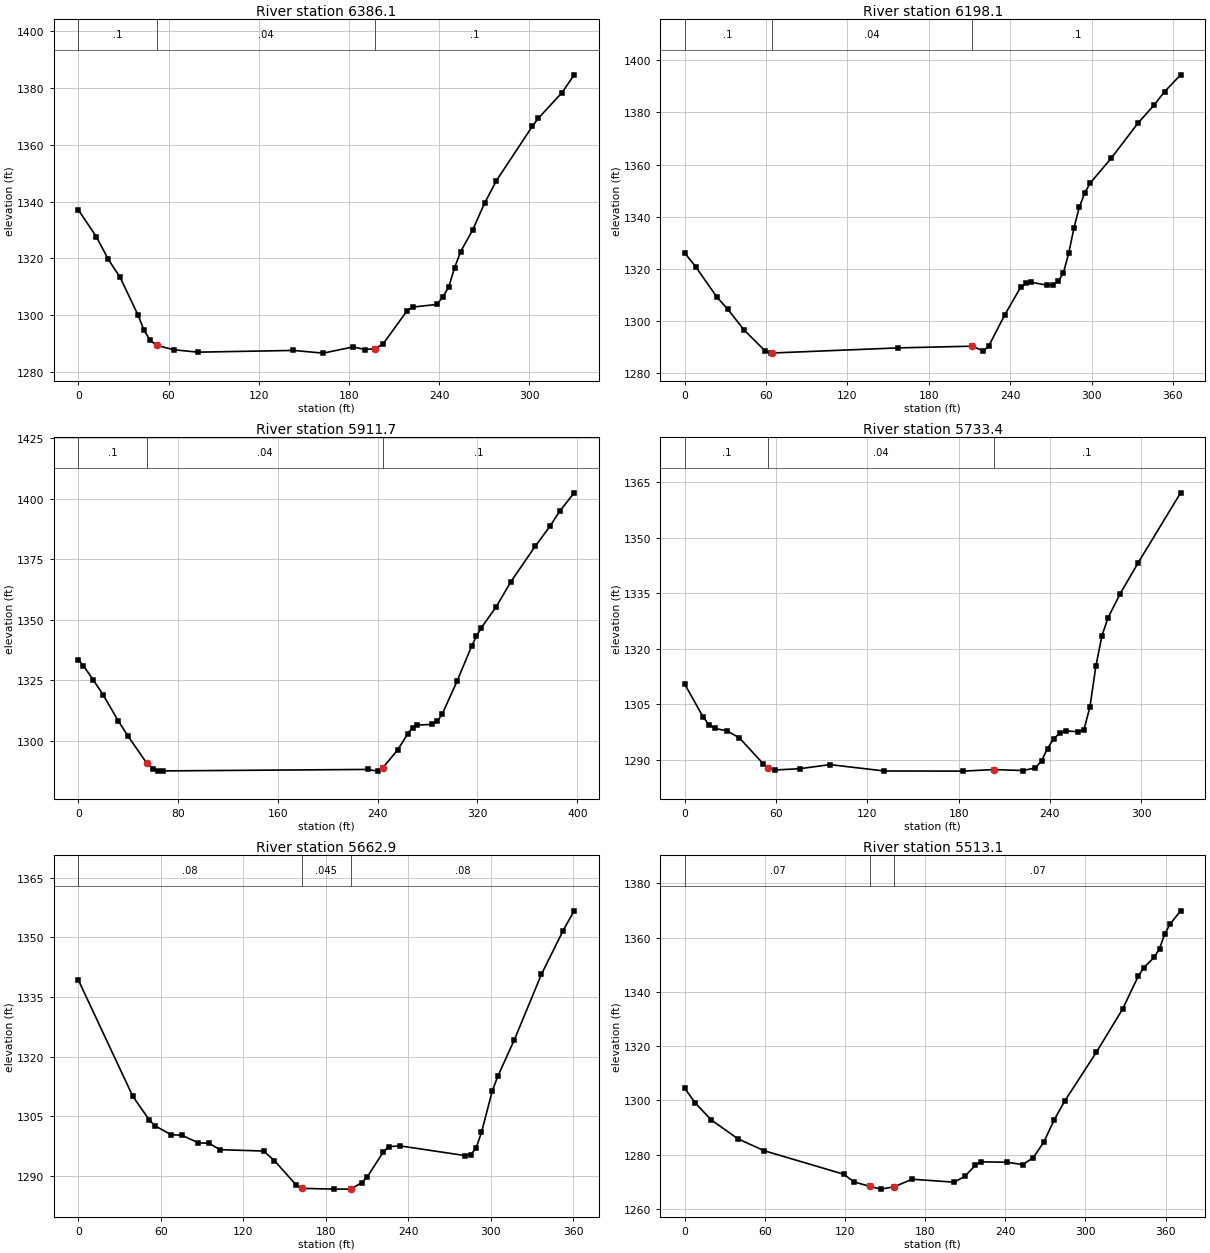
Type RM Length L Ch R = 1 ,6386.1  ,184.4,188,191.6
XS GIS Cut Line= 2
     1799194.861      332898.758     1799420.121      333139.644
#Sta/Elev= 30
       0 1337.05    11.9 1327.69    19.9 1319.68    27.8  1313.3    39.7 1300.07
    43.7 1294.73    47.7 1291.21      521289.408    63.6 1287.85    79.5 1287.01
     143 1287.62   162.9 1286.67   182.8 1288.86   190.7 1287.93     197 1288.22
   202.6 1289.83   218.5 1301.44   222.5 1302.87   238.4 1303.79   242.4 1306.38
   246.4 1309.98   250.3 1316.76   254.3  1322.4   262.2 1329.87   270.2  1339.4
   278.1 1347.34     302 1366.48     306  1369.3   321.8 1378.34   329.8 1384.56
#Mann= 3 , 0 , 0
       0      .1       0      52     .04       0     197      .1       0
Bank Sta=52,197
XS Rating Curve= 0 ,0
Exp/Cntr=0.3,0.1

Type RM Length L Ch R = 1 ,6198.1  ,283.9,286.4,288.6
XS GIS Cut Line= 4
     1799052.933      333001.623     1799086.788      333040.685
     1799196.163      333203.446     1799256.058      333305.008
#Sta/Elev= 30
       0 1326.09       8 1320.88    23.9 1309.08    31.8 1304.49    43.7 1296.65
    59.5 1288.45    63.5 1287.75      641287.785   157.6 1289.76     212 1290.41
   220.3 1288.56   224.3 1290.61     236 1302.43   247.8 1313.07   251.7 1314.51
   255.6 1314.89   267.4 1313.78   271.4 1313.99   275.3 1315.21   279.2  1318.4
   283.2 1326.15   287.1 1335.87     291 1343.74     295 1349.11   298.9 1352.86
   314.6 1362.51   334.2 1375.86     346 1382.75   353.9 1387.97   365.7 1394.41
#Mann= 3 , 0 , 0
       0      .1       0      64     .04       0     212      .1       0
Bank Sta=64,212
XS Rating Curve= 0 ,0
Exp/Cntr=0.3,0.1

Type RM Length L Ch R = 1 ,5911.7  ,179.7,178.3,176.3
XS GIS Cut Line= 4
     1798830.277      333122.717     1798845.902      333172.196
     1798957.881      333384.435     1798998.246      333482.092
#Sta/Elev= 30
       0 1333.45       4 1331.04      12  1325.1      20 1318.85    31.9 1308.29
    39.9 1301.83      551290.612    59.9 1288.49    63.9 1287.61    67.9  1287.5
   231.9 1288.11   239.9 1287.41     2441288.737   255.9 1296.11   263.9 1302.69
   267.9 1305.36   271.9 1306.46   283.9 1306.72   287.9 1307.98   291.9 1311.19
   303.6 1324.56   315.3 1339.07   319.2 1343.23   323.2 1346.78   334.9 1355.24
   346.6 1365.56   366.2 1380.32     378 1388.54   385.8 1394.77   397.5 1402.45
#Mann= 3 , 0 , 0
       0      .1       0      55     .04       0     244      .1       0
Bank Sta=55,244
XS Rating Curve= 0 ,0
Exp/Cntr=0.3,0.1

Type RM Length L Ch R = 1 ,5733.4  ,72.1,70.5,69.6
XS GIS Cut Line= 2
     1798659.704      333220.373     1798832.881      333496.414
#Sta/Elev= 30
       0  1310.4    11.9 1301.64    15.9 1299.42    19.9 1298.44    27.8 1297.78
    35.8 1295.93    51.7 1288.82      551287.619    59.6 1287.22    75.5 1287.55
    95.4 1288.66   131.1 1286.94   182.8  1286.9     2031287.322   222.5 1287.06
   230.5 1287.79   234.5 1289.67   238.4 1293.02   242.4  1295.6   246.4  1297.2
   250.4 1297.77   258.3 1297.57   262.3 1298.02   266.3 1304.29   270.2 1315.32
   274.2 1323.55   278.2  1328.4   286.1 1334.84     298 1343.27   325.9 1362.18
#Mann= 3 , 0 , 0
       0      .1       0      55     .04       0     203      .1       0
Bank Sta=55,203
XS Rating Curve= 0 ,0
Exp/Cntr=0.3,0.1

Type RM Length L Ch R = 1 ,5662.9  ,150,149.8,149.4
XS GIS Cut Line= 2
     1798575.069      333235.998     1798783.402      333530.269
#Sta/Elev= 30
       0 1339.28    39.6 1310.03    51.5 1304.12    55.5 1302.66    67.4 1300.36
    75.3 1300.23    87.2 1298.33    95.1 1298.18     103  1296.6   134.7 1296.25
   142.6 1293.85   158.5 1287.67   162.4 1286.87   186.2 1286.67   198.1 1286.68
     206 1288.26     210  1289.7   221.9 1296.07   225.8 1297.35   233.8 1297.55
   281.3 1295.11   285.3 1295.35   289.2 1296.92   293.2 1300.96   301.1 1311.42
   305.1 1315.08     317 1324.15   336.8  1340.7   352.6 1351.72   360.6 1356.67
#Mann= 3 , 0 , 0
       0     .08       0   162.4    .045       0   198.1     .08       0
Bank Sta=162.4,198.1
XS Rating Curve= 0 ,0
Exp/Cntr=0.3,0.1

Type RM Length L Ch R = 1 ,5513.1  ,194.2,195.6,195.9
XS GIS Cut Line= 3
     1798496.944      333364.904     1798555.538      333463.862
     1798706.579      333670.894
#Sta/Elev= 30
       0 1304.45     7.9 1299.02    19.8 1292.82    39.7 1285.87    59.5 1281.44
     119 1272.79   126.8 1269.92   138.7  1268.3   146.6 1267.29   156.8 1268.15
   170.2 1270.94   201.7 1269.86   209.6 1271.96   217.5 1276.05   221.5 1277.36
   241.2 1277.21     253 1276.32   260.9 1278.87   268.8 1284.61   276.6 1292.81
   284.5 1299.76   308.2 1317.76   327.9 1333.75   339.7 1345.96   343.7 1348.93
   351.6 1352.84   355.5 1355.96   359.4 1361.39   363.4 1365.03   371.3 1369.92
#Mann= 3 , 0 , 0
       0     .07       0   138.7    .045       0   156.8     .07       0
Bank Sta=138.7,156.8
XS Rating Curve= 0 ,0
Exp/Cntr=0.3,0.1

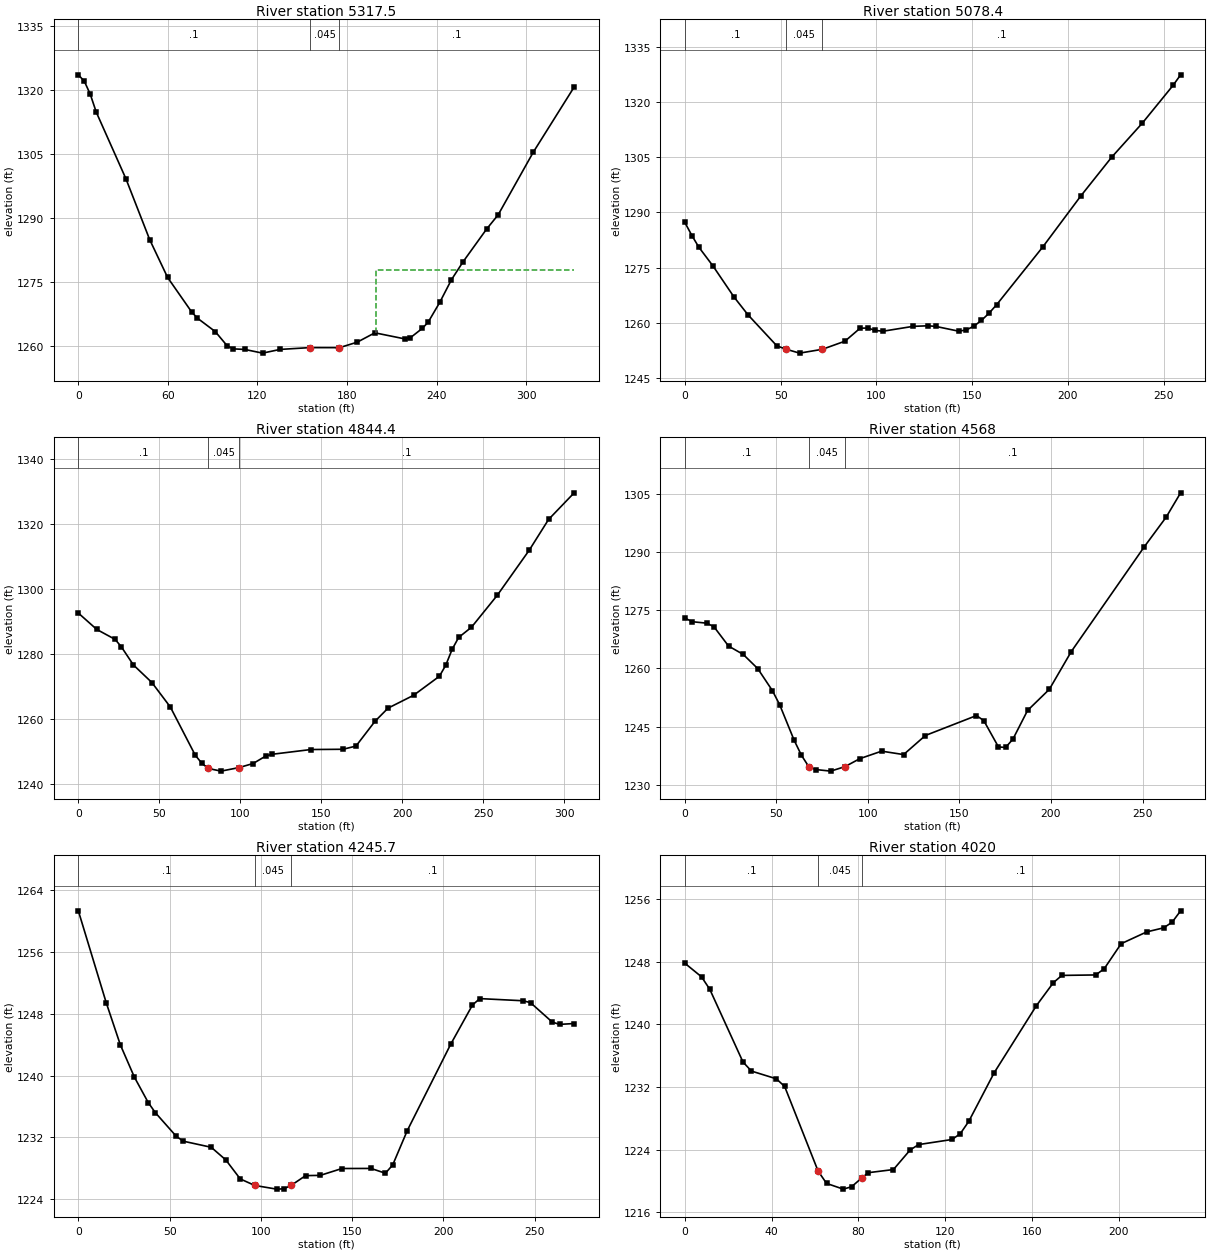
Type RM Length L Ch R = 1 ,5317.5  ,251.9,239.1,222.8
XS GIS Cut Line= 4
     1798341.996      333502.925     1798399.288      333569.331
     1798478.715      333687.821     1798511.267      333784.175
#Sta/Elev= 30
       0 1323.51       4 1322.02       8 1318.96      12 1314.79    31.9 1299.19
    47.8 1284.97    59.8 1276.13    75.8 1268.12    79.7 1266.63    91.7 1263.48
    99.6 1260.19   103.6 1259.44   111.5  1259.3   123.4 1258.44   135.2 1259.31
   155.1 1259.73   174.9 1259.72   186.8    1261   198.6 1263.19   218.5 1261.78
   222.4 1262.04   230.4 1264.23   234.3 1265.67   242.1 1270.32   249.9  1275.6
   257.7  1279.8   273.4 1287.42   281.2 1290.78   304.7 1305.41   332.1 1320.66
#Mann= 3 , 0 , 0
       0      .1       0   155.1    .045       0   174.9      .1       0
#XS Ineff= 2 , 0
                          199.34         1277.86
Permanent Ineff=
       F       F
Bank Sta=155.1,174.9
XS Rating Curve= 0 ,0
Exp/Cntr=0.3,0.1

Type RM Length L Ch R = 1 ,5078.4  ,231.5,234,238.6
XS GIS Cut Line= 4
     1798237.829      333781.571     1798274.288       333806.31
     1798379.756      333840.164     1798481.319        333862.3
#Sta/Elev= 30
       0 1287.32     3.7 1283.74     7.3 1280.59    14.7 1275.47    25.7 1267.02
      33 1262.18      48 1253.78    52.7 1252.87    59.9 1251.78    71.8 1252.82
    83.6 1255.03    91.5 1258.55    95.5  1258.6    99.4 1257.96   103.4 1257.73
   119.2 1259.06   127.1 1259.21   131.1 1259.03     143 1257.74   146.9 1258.08
   150.9 1259.11   154.8 1260.66   158.8 1262.63   162.8 1264.96   186.8  1280.6
   206.8 1294.56   222.8 1305.02   238.8 1314.28   254.8 1324.51   258.8 1327.41
#Mann= 3 , 0 , 0
       0      .1       0    52.7    .045       0    71.8      .1       0
Bank Sta=52.7,71.8
XS Rating Curve= 0 ,0
Exp/Cntr=0.3,0.1

Type RM Length L Ch R = 1 ,4844.4  ,278.4,276.5,273.7
XS GIS Cut Line= 3
     1798149.288      333988.602     1798203.975      334022.456
     1798416.215      334138.342
#Sta/Elev= 30
       0  1292.7    11.4 1287.66    22.7 1284.61    26.5 1282.36      34 1276.75
    45.4 1271.35    56.8 1263.82    72.2 1248.99    76.2 1246.55    80.2 1244.93
    88.1 1244.11    99.2  1245.2   107.9 1246.45   115.8 1248.78   119.8  1249.3
   143.6 1250.75   163.4 1250.83   171.4 1251.81   183.2 1259.46   191.2 1263.47
     207 1267.43   222.9 1273.27   226.8 1276.63   230.8 1281.58   234.8 1285.21
   242.7 1288.34   258.6 1298.14   278.4 1312.05   290.3 1321.47   306.1 1329.66
#Mann= 3 , 0 , 0
       0      .1       0    80.2    .045       0    99.2      .1       0
Bank Sta=80.2,99.2
XS Rating Curve= 0 ,0
Exp/Cntr=0.3,0.1

Type RM Length L Ch R = 1 ,4568    ,310.2,322.3,334.1
XS GIS Cut Line= 2
     1798051.631      334256.831     1798301.631      334360.998
#Sta/Elev= 30
       0 1272.98       4 1272.02      12 1271.64    15.9 1270.73    23.9 1265.75
    31.9  1263.6    39.8 1259.97    47.8 1254.31    51.8 1250.67    59.7 1241.53
    63.7 1237.64    67.7 1234.71    71.7 1233.96    79.7 1233.56    87.5 1234.72
    95.6 1236.77   107.5  1238.7   119.5 1237.82   131.4 1242.73   159.3 1247.86
   163.3 1246.56   171.3 1239.79   175.2 1239.65   179.2 1241.79   187.2 1249.17
   199.1 1254.62   211.1 1264.35   250.9 1291.27   262.9 1298.93   270.8 1305.19
#Mann= 3 , 0 , 0
       0      .1       0    67.7    .045       0    87.5      .1       0
Bank Sta=67.7,87.5
XS Rating Curve= 0 ,0
Exp/Cntr=0.3,0.1

Type RM Length L Ch R = 1 ,4245.7  ,214.6,225.7,235.9
XS GIS Cut Line= 3
     1797894.079       334456.05     1797929.236      334519.852
     1798050.329      334677.404
#Sta/Elev= 30
       0 1261.35    15.3 1249.43      23    1244    30.7 1239.81    38.3 1236.51
    42.2  1235.2    53.7 1232.13    57.5 1231.51    72.8 1230.72    80.8 1229.08
    88.7 1226.62    96.6 1225.78   108.6  1225.3   112.6 1225.34   116.6 1225.79
   124.5 1227.05   132.5 1227.08   144.4 1227.97   160.3 1227.98   168.2 1227.36
   172.2 1228.43   180.2 1232.89     204 1244.08   215.9 1249.15   219.9 1249.98
   243.7  1249.7   247.7 1249.45   259.6 1246.94   263.6 1246.64   271.6 1246.75
#Mann= 3 , 0 , 0
       0      .1       0    96.6    .045       0   116.6      .1       0
Bank Sta=96.6,116.6
XS Rating Curve= 0 ,0
Exp/Cntr=0.3,0.1

Type RM Length L Ch R = 1 ,4020    ,296.3,295.8,288.8
XS GIS Cut Line= 4
     1797743.038      334603.185     1797759.965       334650.06
      1797775.59      334729.487      1797806.84      334821.935
#Sta/Elev= 30
       0  1247.8     7.7 1246.06    11.5 1244.47    26.8 1235.18    30.7 1234.02
    42.2 1233.03      46 1232.05    61.4 1221.25    65.3 1219.67      73 1218.94
    76.8 1219.24    81.5 1220.36    84.5 1221.04    96.1 1221.44   103.8 1223.94
   107.7 1224.63   123.1 1225.28   126.9 1226.02   130.8 1227.59   142.5  1233.8
     162 1242.39   169.8 1245.32   173.7 1246.24   189.3  1246.3   193.2 1247.09
     201 1250.29   212.8  1251.8   220.6 1252.32   224.5 1253.04   228.4 1254.49
#Mann= 3 , 0 , 0
       0      .1       0    61.4    .045       0    81.5      .1       0
Bank Sta=61.4,81.5
XS Rating Curve= 0 ,0
Exp/Cntr=0.3,0.1

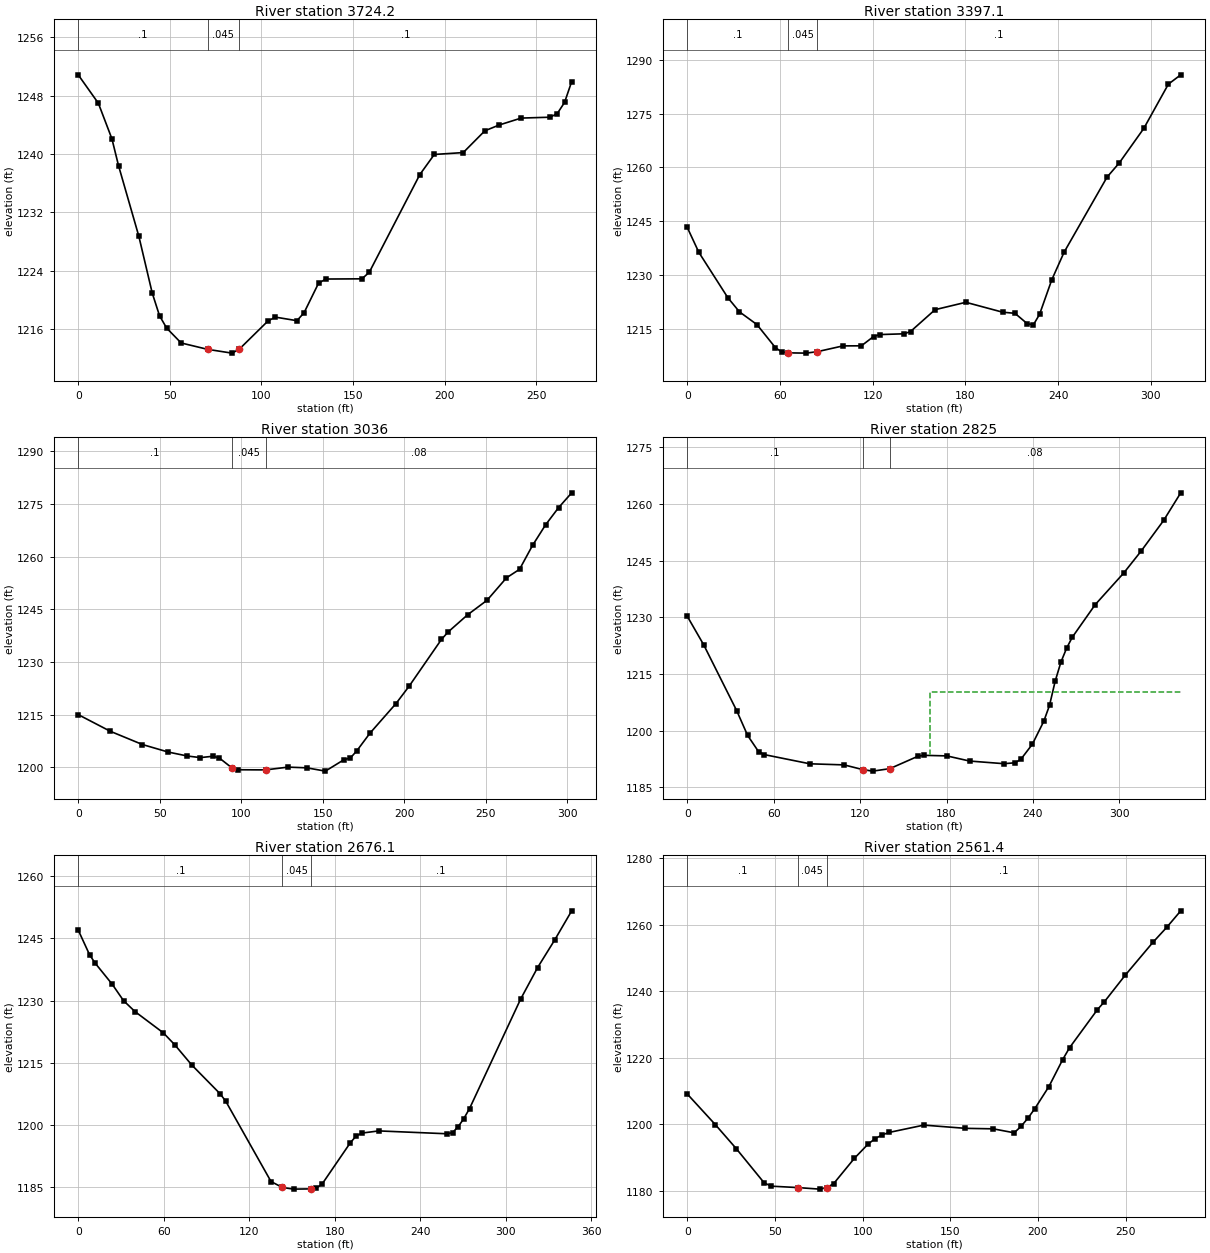
Type RM Length L Ch R = 1 ,3724.2  ,334.9,327.1,321.9
XS GIS Cut Line= 3
     1797493.038      334721.675     1797503.454      334760.737
     1797598.506      334969.071
#Sta/Elev= 30
       0 1250.84      11 1246.95    18.4 1242.08      22 1238.42    33.1 1228.74
    40.4 1220.98    44.4 1217.86    48.3 1216.17    56.2 1214.14    70.6 1213.27
    83.9 1212.75    87.8 1213.26   103.6 1217.15   107.6 1217.68   119.4 1217.19
   123.3 1218.28   131.2 1222.32   135.2 1222.89   154.9 1222.92   158.9 1223.82
   186.5 1237.19   194.4 1239.94   210.2  1240.2     222 1243.18   229.9 1243.98
   241.8 1244.92   257.6 1245.04   261.5 1245.53   265.5 1247.06   269.4 1249.92
#Mann= 3 , 0 , 0
       0      .1       0    70.6    .045       0    87.8      .1       0
Bank Sta=70.6,87.8
XS Rating Curve= 0 ,0
Exp/Cntr=0.3,0.1

Type RM Length L Ch R = 1 ,3397.1  ,362.2,361.1,360
XS GIS Cut Line= 3
     1797197.465      334907.873     1797230.017      334939.123
     1797374.548      335172.196
#Sta/Elev= 30
       0 1243.27     7.5 1236.31    26.3 1223.63    33.8  1219.7    45.1 1216.15
      57 1209.74      61 1208.52      65 1208.26    76.9 1208.18    84.1 1208.58
   100.8  1210.2   112.7 1210.22   120.6 1212.82   124.6 1213.36   140.5 1213.58
   144.5 1214.21   160.4 1220.31   180.3 1222.37   204.1 1219.61   212.1 1219.29
     220 1216.42     224 1216.07     228 1218.98   235.9 1228.62   243.9 1236.35
   271.7 1257.31   279.6 1261.27   295.5 1270.92   311.4 1283.27   319.4 1285.87
#Mann= 3 , 0 , 0
       0      .1       0      65    .045       0    84.1      .1       0
Bank Sta=65,84.1
XS Rating Curve= 0 ,0
Exp/Cntr=0.3,0.1

Type RM Length L Ch R = 1 ,3036    ,215.1,211.1,206.8
XS GIS Cut Line= 4
     1796977.413      335135.737     1797004.756      335213.862
     1797052.933      335282.873     1797116.736      335402.664
#Sta/Elev= 30
       0    1215    19.7 1210.25    39.4 1206.48    55.2 1204.34      67 1203.21
    74.9 1202.76    82.8 1203.15    86.6 1202.63    94.2 1199.86    98.1  1199.3
   114.9 1199.26   128.7 1200.05   140.2 1199.85   151.6 1198.91   163.1 1202.19
   166.9 1202.63   170.9  1204.7   178.9 1209.68   194.9 1218.13   202.9 1223.04
   222.8  1236.4   226.8 1238.48   238.8  1243.4   250.8 1247.56   262.7 1253.94
   270.7 1256.36   278.7 1263.19   286.7 1269.04   294.7 1273.95   302.7 1278.14
#Mann= 3 , 0 , 0
       0      .1       0    94.2    .045       0   114.9     .08       0
Bank Sta=94.2,114.9
XS Rating Curve= 0 ,0
Exp/Cntr=0.3,0.1

Type RM Length L Ch R = 1 ,2825    ,148.3,148.9,149.6
XS GIS Cut Line= 3
     1796759.314      335279.618     1796798.376         335310.
      1797006.71      335516.163
#Sta/Elev= 30
       0 1230.31    11.4 1222.76    34.3 1205.34    41.9 1198.77    49.5 1194.48
    53.4  1193.7    85.1 1191.26   108.9 1190.97   121.8 1189.73   128.7 1189.32
   140.6 1189.97   160.4  1193.3   164.4  1193.5   180.2 1193.35     196 1191.99
   219.8 1191.29   227.7 1191.53   231.7  1192.5   239.6 1196.45   247.5  1202.5
   251.5 1206.73   255.4 1213.09   259.4 1218.17   263.4 1221.89   267.3 1224.76
   283.2 1233.38     303 1241.75   314.9 1247.46   330.7 1255.66   342.6 1262.98
#Mann= 3 , 0 , 0
       0      .1       0   121.8    .045       0   140.6     .08       0
#XS Ineff= 2 , 0
                          168.64         1210.19
Permanent Ineff=
       F       F
Bank Sta=121.8,140.6
XS Rating Curve= 0 ,0
Exp/Cntr=0.3,0.1

Type RM Length L Ch R = 1 ,2676.1  ,112.7,114.6,116.6
XS GIS Cut Line= 2
     1796644.079      335359.696     1796883.663      335609.696
#Sta/Elev= 30
       0 1247.01       8 1241.03    11.9 1239.02    23.9 1233.91    31.8 1229.97
    39.8 1227.34    59.7  1222.2    67.7 1219.33    79.6 1214.46    99.5  1207.5
   103.5  1205.7   135.3 1186.28   143.3 1184.85   151.2 1184.45   163.2 1184.51
   167.2 1184.74   171.1 1185.65     191 1195.67     195 1197.26     199 1197.98
   210.9 1198.51   258.7 1197.82   262.7 1198.11   266.7 1199.55   270.6 1201.48
   274.6  1203.9   310.4  1230.3   322.4 1237.97   334.3 1244.58   346.3 1251.66
#Mann= 3 , 0 , 0
       0      .1       0   143.3    .045       0   163.2      .1       0
Bank Sta=143.3,163.2
XS Rating Curve= 0 ,0
Exp/Cntr=0.3,0.1

Type RM Length L Ch R = 1 ,2561.4  ,191.3,197,202.5
XS GIS Cut Line= 3
     1796638.871      335510.737     1796663.611      335536.779
     1796817.256      335728.185
#Sta/Elev= 30
       0 1209.15      16 1199.96    27.9 1192.77    43.8 1182.51    47.8 1181.48
    62.9 1181.06    75.5 1180.59    79.5 1181.06    83.4 1182.19    95.3 1189.84
   103.2 1194.16   107.2 1195.76   111.1 1196.87   115.1 1197.61   134.9 1199.81
   158.6 1198.84   174.5 1198.69   186.4  1197.5   190.3 1199.41   194.3 1201.91
   198.2 1204.77   206.2 1211.36   214.1  1219.5     218 1223.05   233.9 1234.49
   237.8  1236.8   249.7 1244.79   265.5 1254.66   273.4 1259.18   281.4 1264.14
#Mann= 3 , 0 , 0
       0      .1       0    62.9    .045       0    79.5      .1       0
Bank Sta=62.9,79.5
XS Rating Curve= 0 ,0
Exp/Cntr=0.3,0.1

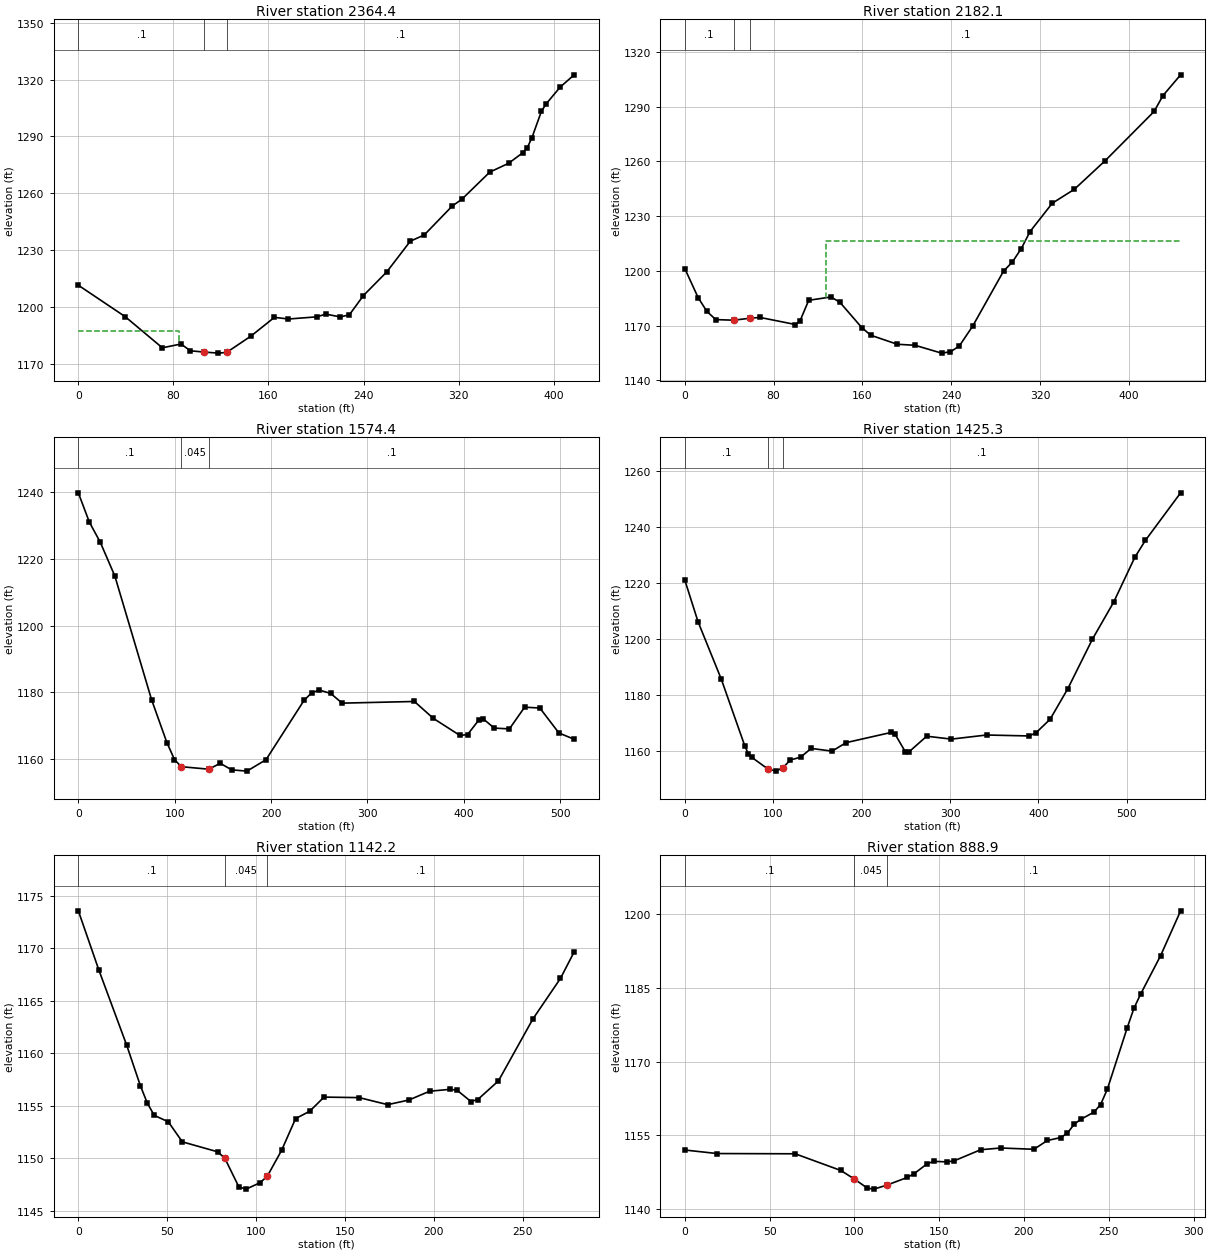
Type RM Length L Ch R = 1 ,2364.4  ,187.4,182.4,175.4
XS GIS Cut Line= 3
     1796506.058      335594.071     1796574.852      335748.368
      1796702.89      335961.041
#Sta/Elev= 30
       0  1211.4    39.3 1194.86    70.7 1178.36    86.4 1180.37    94.3 1176.77
   106.1  1176.1   117.9 1175.55   124.8 1175.92   145.4 1184.62     165 1194.44
   176.8 1193.56   200.5  1194.7   208.3 1196.15   220.2 1194.68     228 1195.72
   239.9 1205.96   259.6 1218.48   279.3 1234.63   291.1 1237.96   314.7 1253.26
   322.6 1256.73   346.2 1271.12     362 1275.76   373.8 1281.25   377.8 1284.05
   381.7 1289.35   389.6 1303.14   393.5 1307.04   405.4 1315.98   417.2 1322.48
#Mann= 3 , 0 , 0
       0      .1       0   106.1    .045       0   124.8      .1       0
#XS Ineff= 2 , 0
           85.03 1187.32
Permanent Ineff=
       F       F
Bank Sta=106.1,124.8
XS Rating Curve= 0 ,0
Exp/Cntr=0.3,0.1

Type RM Length L Ch R = 1 ,2182.1  ,594.7,607.7,619.9
XS GIS Cut Line= 2
     1796355.668      335689.774     1796583.532      336073.888
#Sta/Elev= 30
       0 1201.32      12 1185.39    19.9 1177.84    27.9 1173.34      44 1173.01
      59 1174.12    67.8 1174.52    99.7 1170.64   103.7 1172.51   111.6 1183.91
   131.6 1185.72   139.6 1182.89   159.5  1168.9   167.5 1164.78   191.4 1159.83
   207.4 1159.27   231.3 1154.98   239.3 1155.72   247.2 1158.84   259.2 1169.67
   287.1 1199.88   295.1 1204.91   303.1 1212.26     311 1221.57     331 1237.08
   350.9 1244.71   378.8 1260.46   422.7 1287.31   430.7 1296.03   446.6 1307.39
#Mann= 3 , 0 , 0
       0      .1       0      44    .045       0      59      .1       0
#XS Ineff= 2 , 0
                          127.55         1216.22
Permanent Ineff=
       F       F
Bank Sta=44,59
XS Rating Curve= 0 ,0
Exp/Cntr=0.3,0.1

Type RM Length L Ch R = 1 ,1574.4  ,143.8,149.1,154.2
XS GIS Cut Line= 4
     1795886.267      335975.581       1795907.1      336044.592
     1795930.538      336189.123     1795981.319      336480.789
#Sta/Elev= 30
       0 1239.83    11.4 1231.07    22.8 1224.99    37.9 1214.88      76 1177.83
    91.9 1164.96    99.8 1159.87   106.8 1157.73   135.4 1156.98   147.3 1158.74
   159.2 1156.78     175  1156.4   194.8 1159.83   234.3 1177.63   242.2 1179.88
   250.1  1180.7   261.9 1179.69   273.8 1176.78   348.8 1177.28   368.5  1172.2
   396.1 1167.09     404 1167.37   415.9 1171.81   419.8 1172.16   431.7  1169.3
   447.4 1169.06   463.2 1175.57     479 1175.32   498.8 1167.83   514.6 1165.96
#Mann= 3 , 0 , 0
       0      .1       0   106.8    .045       0   135.4      .1       0
Bank Sta=106.8,135.4
XS Rating Curve= 0 ,0
Exp/Cntr=0.3,0.1

Type RM Length L Ch R = 1 ,1425.3  ,277.7,283.1,288.4
XS GIS Cut Line= 4
       1795782.1      335988.602     1795769.079      336047.196
     1795757.361      336216.467     1795741.736      336547.196
#Sta/Elev= 30
       0  1221.1      15 1206.19    41.3 1185.68    67.9 1161.83    71.9 1159.03
    75.8 1157.77      94 1153.62   103.4 1152.86   111.3 1154.14   119.2 1156.82
     131 1157.84   142.9 1160.97   166.6    1160   182.4 1163.03   233.7  1166.7
   237.7 1166.12   249.6 1159.68   253.6 1159.75   273.6 1165.33   301.5 1164.29
   341.4 1165.76   389.3 1165.42   397.2 1166.54   413.2 1171.39   433.1 1182.24
   461.1 1200.02     485 1213.17   508.9 1229.16   520.9 1235.24   560.8 1252.25
#Mann= 3 , 0 , 0
       0      .1       0      94    .045       0   111.3      .1       0
Bank Sta=94,111.3
XS Rating Curve= 0 ,0
Exp/Cntr=0.3,0.1

Type RM Length L Ch R = 1 ,1142.2  ,250.8,253.3,254.8
XS GIS Cut Line= 4
     1795529.496      335928.706     1795508.663      335970.373
     1795465.694      336107.092     1795434.444      336190.425
#Sta/Elev= 30
       0 1173.57    11.6 1167.91    27.2 1160.78    34.9 1156.92    38.8 1155.27
    42.7  1154.1    50.6 1153.49    58.5 1151.58    78.4 1150.63    82.4 1150.02
    90.3 1147.29    94.4 1147.08   102.3  1147.7   106.3 1148.31   114.3 1150.76
   122.2 1153.79   130.2  1154.5   138.2 1155.84     158 1155.79     174 1155.12
   185.9 1155.56   197.6  1156.4   209.2 1156.58   213.1 1156.49   220.8 1155.42
   224.7 1155.61   236.3 1157.38   255.7 1163.28   271.2 1167.14   278.9 1169.66
#Mann= 3 , 0 , 0
       0      .1       0    82.4    .045       0   106.3      .1       0
Bank Sta=82.4,106.3
XS Rating Curve= 0 ,0
Exp/Cntr=0.3,0.1

Type RM Length L Ch R = 1 ,888.9   ,122.2,125.9,128
XS GIS Cut Line= 3
     1795300.329      335838.862     1795265.173      335919.592
     1795187.048      336108.394
#Sta/Elev= 30
       0 1151.99    19.1 1151.27    65.1 1151.22      92 1147.82    99.8 1146.12
   107.7 1144.21   111.6 1144.02   119.4 1144.87   131.3 1146.41   135.2 1147.16
   143.1 1149.23     147 1149.68   154.8 1149.57   158.8 1149.78   174.5 1152.05
   186.3  1152.4   205.9 1152.14   213.8 1153.93   221.6 1154.52   225.6 1155.41
   229.5 1157.19   233.4 1158.22   241.3 1159.71   245.2 1161.25   249.2  1164.4
   260.9  1176.9   264.9  1180.9   268.8 1183.75   280.6  1191.6   292.4 1200.73
#Mann= 3 , 0 , 0
       0      .1       0    99.8    .045       0   119.4      .1       0
Bank Sta=99.8,119.4
XS Rating Curve= 0 ,0
Exp/Cntr=0.3,0.1

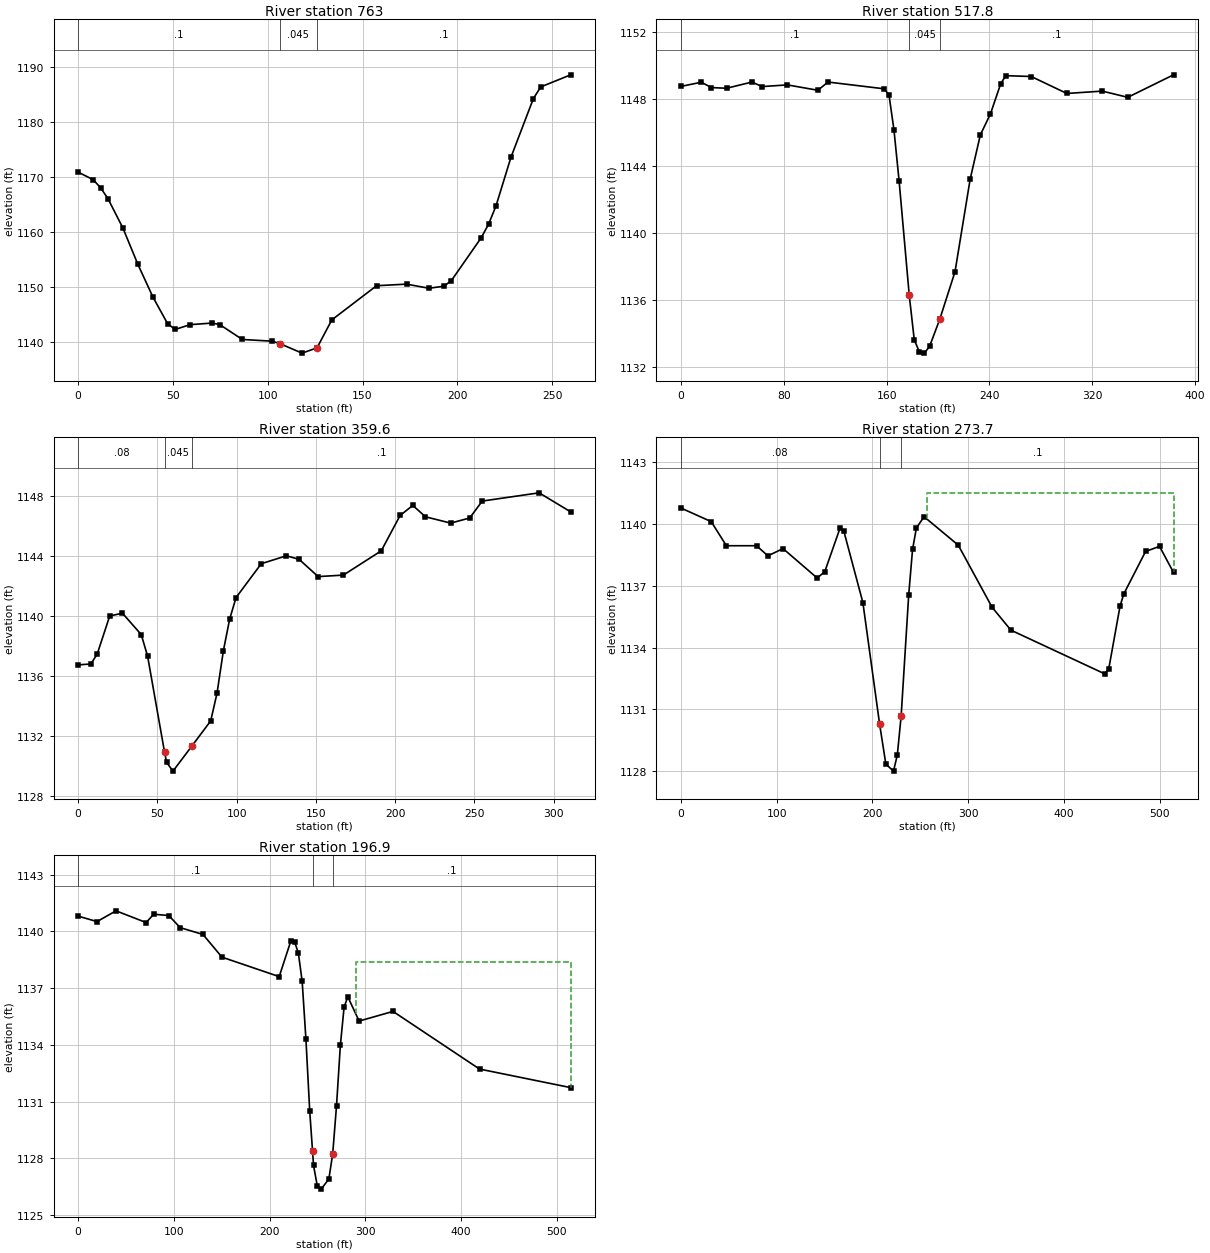
Type RM Length L Ch R = 1 ,763     ,236.8,245.2,253.9
XS GIS Cut Line= 3
      1795181.84      335816.727     1795171.423      335850.581
      1795063.35      336047.196
#Sta/Elev= 30
       0 1170.85     7.9 1169.49    11.8 1168.03    15.7 1166.04    23.6  1160.7
    31.5 1154.09    39.4 1148.18    47.2 1143.29    51.2 1142.27      59 1143.13
    70.8 1143.43    74.8 1143.12    86.6 1140.44   102.3 1140.13   106.3  1139.7
   118.1 1137.96     126 1138.92   133.8    1144   157.4 1150.21   173.2  1150.5
     185 1149.75   192.9 1150.12   196.8 1151.11   212.6 1158.93   216.5  1161.4
   220.4 1164.71   228.3 1173.56   240.1 1184.21     244 1186.34   259.8 1188.54
#Mann= 3 , 0 , 0
       0      .1       0   106.3    .045       0     126      .1       0
Bank Sta=106.3,126
XS Rating Curve= 0 ,0
Exp/Cntr=0.3,0.1

Type RM Length L Ch R = 1 ,517.8   ,161.8,158.2,154.5
XS GIS Cut Line= 3
     1795103.715      335704.748     1794953.975      335765.946
     1794780.798      335903.967
#Sta/Elev= 30
       0 1148.73    15.8 1148.98    23.7 1148.66    35.5 1148.62    55.2 1148.99
    63.1 1148.72    82.8 1148.82   106.5  1148.5   114.4 1148.99   157.8 1148.59
   161.8 1148.24   165.7 1146.14   169.7  1143.1   177.6 1136.28   181.5 1133.63
   185.5 1132.91   189.4 1132.84   193.4 1133.24   201.3 1134.85   213.2 1137.69
     225 1143.21   232.9 1145.84   240.8  1147.1   248.8  1148.9   252.7 1149.37
   272.5 1149.32   300.2 1148.31   327.8 1148.45   347.6 1148.08   383.2 1149.42
#Mann= 3 , 0 , 0
       0      .1       0   177.6    .045       0   201.3      .1       0
Bank Sta=177.6,201.3
XS Rating Curve= 0 ,0
Exp/Cntr=0.3,0.1

Type RM Length L Ch R = 1 ,359.6   ,70.2,85.9,100.4
XS GIS Cut Line= 2
     1794851.111      335638.342     1794642.777       335868.81
#Sta/Elev= 30
       0 1136.75       8 1136.81      12 1137.47    19.9 1140.01    27.9  1140.2
    39.8 1138.77    43.8 1137.33    54.5 1130.92    55.8 1130.24    59.8 1129.66
    71.7 1131.33    83.6 1133.01    87.6 1134.86    91.6 1137.69    95.6 1139.82
    99.6 1141.24   115.5  1143.5   131.4 1144.03   139.4 1143.79   151.4 1142.64
   167.3 1142.74   191.2 1144.36   203.1 1146.72   211.1 1147.39   219.1 1146.63
     235 1146.21     247 1146.55   254.9 1147.68   290.8 1148.23   310.7 1146.96
#Mann= 3 , 0 , 0
       0     .08       0    54.5    .045       0    71.7      .1       0
Bank Sta=54.5,71.7
XS Rating Curve= 0 ,0
Exp/Cntr=0.3,0.1

Type RM Length L Ch R = 1 ,273.7   ,79.9,76.8,74.4
XS GIS Cut Line= 6
     1794940.954      335571.935     1794851.111      335601.883
     1794791.215      335622.717     1794680.538      335656.571
     1794490.433      335720.373     1794451.371      335729.487
#Sta/Elev= 30
       0 1140.78    31.6 1140.12    47.4 1138.95    78.9 1138.95    90.8 1138.46
   106.6 1138.81   142.3 1137.38   150.2 1137.69   166.1  1139.8   170.1 1139.66
     190 1136.19   207.5 1130.28     214 1128.34     222    1128     226 1128.79
     230 1130.69   237.9 1136.58   241.9 1138.77   245.9 1139.81   253.9 1140.36
   289.6 1138.98     325 1135.96   344.6 1134.85   442.9 1132.72   446.9 1132.98
   458.7 1136.03   462.6 1136.61   485.3 1138.67   499.9 1138.92   514.5 1137.65
#Mann= 3 , 0 , 0
       0     .08       0   207.5    .045       0     230      .1       0
#XS Ineff= 2 , 0
                          256.69         1141.52
Permanent Ineff=
       F       F
Bank Sta=207.5,230
XS Rating Curve= 0 ,0
Exp/Cntr=0.3,0.1

Type RM Length L Ch R = 1 ,196.9   ,196.8,196.9,196.3
XS GIS Cut Line= 6
     1794929.236      335501.623     1794839.392      335531.571
     1794779.496      335552.404     1794668.819      335586.258
     1794478.715       335650.06     1794439.652      335659.175
#Sta/Elev= 30
       0 1140.81    19.7 1140.52    39.5 1141.09      71 1140.47    78.9 1140.91
    94.7 1140.84   106.6  1140.2   130.4 1139.84   150.2 1138.64     210 1137.61
     222 1139.47     226 1139.46     230 1138.86     234 1137.36   237.9 1134.32
   241.9 1130.49   244.8 1128.41   245.9 1127.62   249.9 1126.51   253.9 1126.37
   261.9 1126.91   265.9 1128.24   269.9 1130.79   273.9 1133.98   277.8    1136
   281.7 1136.54   293.5 1135.26   328.9 1135.77   419.3 1132.72   514.5 1131.74
#Mann= 3 , 0 , 0
       0      .1       0   244.8    .045       0   265.9      .1       0
#XS Ineff= 2 , 0
                          290.17         1138.37
Permanent Ineff=
       F       F
Bank Sta=244.8,265.9
XS Rating Curve= 0 ,0
Exp/Cntr=0.3,0.1

Chan Stop Cuts=-1
Use User Specified Reach Order=0
Composite Channel Slope=5